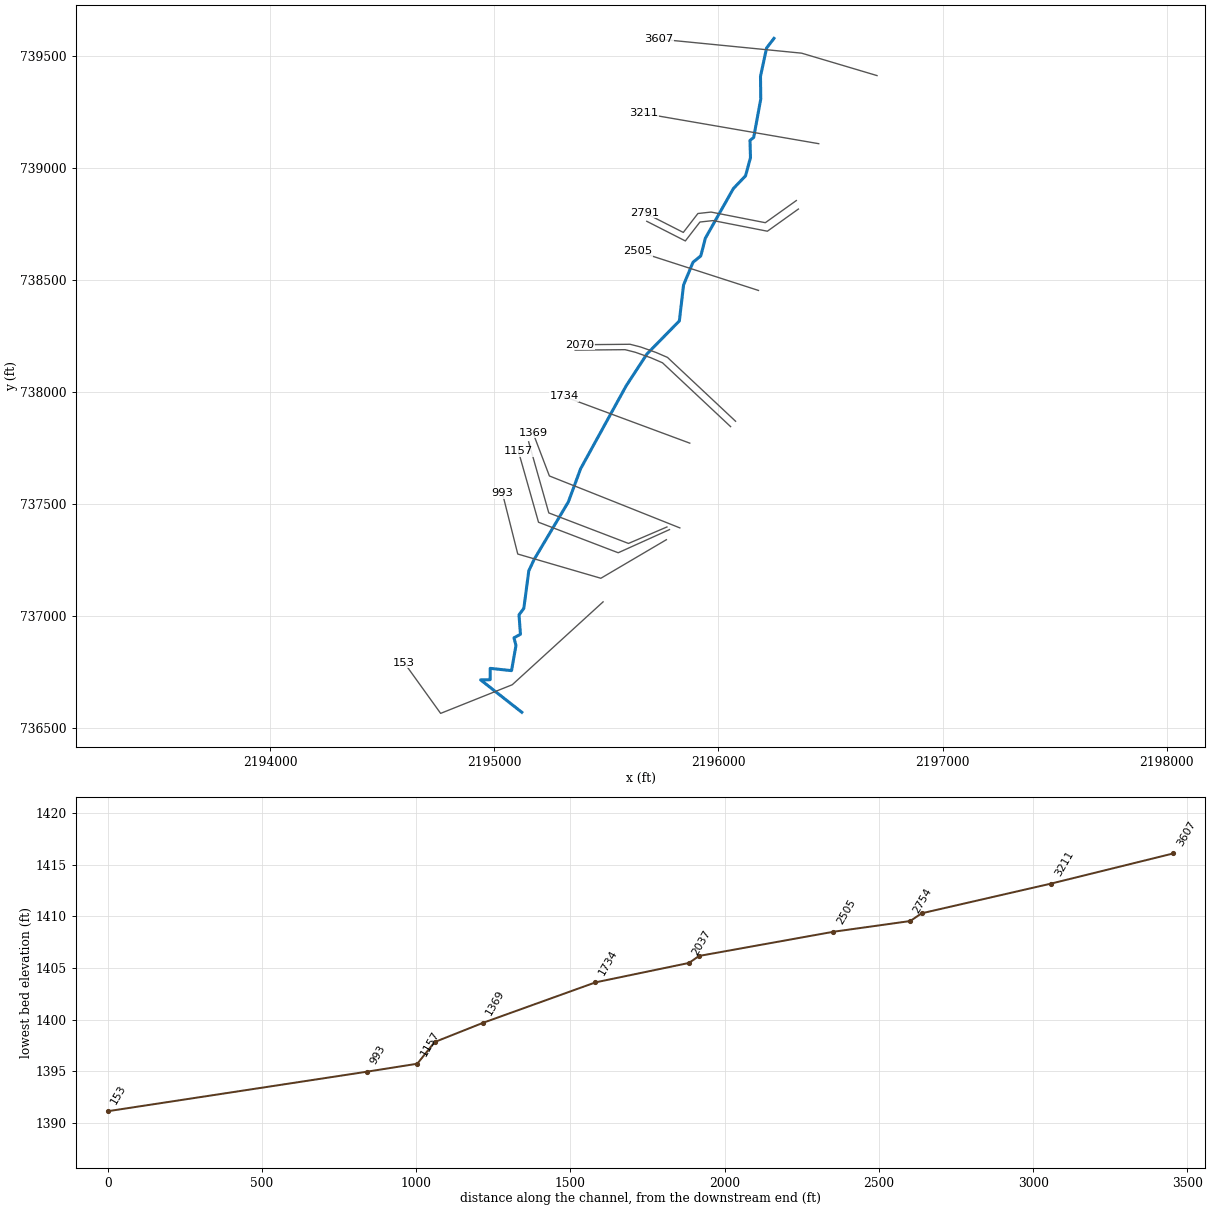
--- BUCKHANRT1.prj (project) ---

Proj Title=BUCKHANRT1
Current Plan=p01
Default Exp/Contr=0,0
English Units
Geom File=g01
Flow File=f01
Plan File=p01
BEGIN DESCRIPTION:
----------MODELED AS PART OF WVEMD CTP PROGRAM, 2022---------
AFH study
Upshur County, WV
HEC-RAS Version: RAS 6.3
Vertical Datum: NAVD88
Projection: NAD 1983 StatePlane West Virginia S FIPS 4702 (US Feet)
Terrain: 1-meter LIDAR (FEMA Region III 3DEP collected 2016-2018)
Land Use: 2019 NLCD
Hydrologic Method:
WV SIR2010-5033 regression equations
Additional Model Notes:
None
END DESCRIPTION:
DSS Export Rating Curves= 0
DSS Export Rating Curve Sorted= 0
DSS Export Volume Flow Curves= 0
DXF OffsetX= 0
DXF OffsetY= 0
DXF ScaleX= 0
DXF ScaleY= 0

--- BUCKHANRT1.p01 (plan) ---

Plan Title=Floodplain
Program Version=4.00
Geom File=g01
Flow File=f01
K Sum by GR=0
Std Step Tol=0.01
Critical Tol=0.01
Num of Std Step Trials=20
Max Error Tol=0.3
Flow Tol Ratio=0.001
Split Flow NTrial=30
Split Flow Tol=0.02
Split Flow Ratio=0.02
Log Output Level=0
Friction Slope Method=1
Unsteady Friction Slope Method=2
Unsteady Bridges Friction Slope Method=1
Global Log Level=0
CheckData=False
Run HTab=0
Run UNet=0
Run PostProcess=0
UNET Theta=0
UNET Theta Warmup=0
UNET ZTol=0
UNET ZSATol=0
UNET MxIter=0
UNET MaxInSteps=0
UNET DtIC=0
UNET DtMin=0
UNET MaxCRTS=0
UNET WFStab=0
UNET SFStab=0
UNET WFX=0
UNET SFX=0
UNET DSS MLevel=0
UNET DZMax Abort=0
UNET Convert EG Bridges=0
UNET Use Existing IB Tables=0
UNET Froude Limit=0
UNET Froude Power=0
Write IC File=0
Echo Input=False
Echo Output=False
Write Detailed=0

--- BUCKHANRT1.f01 (steady flow) ---

Flow Title=Flows
Program Version=6.31
Number of Profiles= 1
Profile Names=01pct
River Rch & RM=BUCKHANRT1,Main            ,3607
     137
River Rch & RM=BUCKHANRT1,Main            ,2070
     158
Boundary for River Rch & Prof#=BUCKHANRT1,Main            , 1
Up Type= 0
Dn Type= 3
Dn Slope=0.00499
DSS Import GetInterval= 0
DSS Import GetPeak= 0
DSS Import FillOption= 0

--- BUCKHANRT1.g01 (geometry) ---

Geom Title=Geometry
Program Version=6.31

River Reach=BUCKHANRT1      ,Main
Reach XY= 30
     2196247.641      739577.6052196214.54157246739534.228617081
2196187.43129367739408.1640446272196188.56936785739306.431158993
2196157.05902854739135.0439858082196140.55386684739122.204049057
 2196142.7064819739045.064558799     2196120.641      738963.697
2196066.50518587738907.1083483362195941.46734322738685.514817131
     2195921.157      738606.5932195886.41492102738578.179905934
2195844.17343984 738476.73110277 2195825.3517438738316.109601789
2195681.15050864738169.0555671422195588.03920438738026.303597667
2195384.72100536737656.0873812182195330.31259263737508.567664236
     2195177.731      737251.8942195153.72210962 737200.82723373
 2195131.5143038737033.2998931872195110.05172636737004.086940565
2195116.46069046736917.6404481142195087.54582919736901.543515037
2195096.48856979 736867.710146442195076.63934637736755.149622204
 2194981.5333001736765.2102053772194981.26501788736714.504866184
2194938.74228634 736713.83416064     2195122.445       736569.25

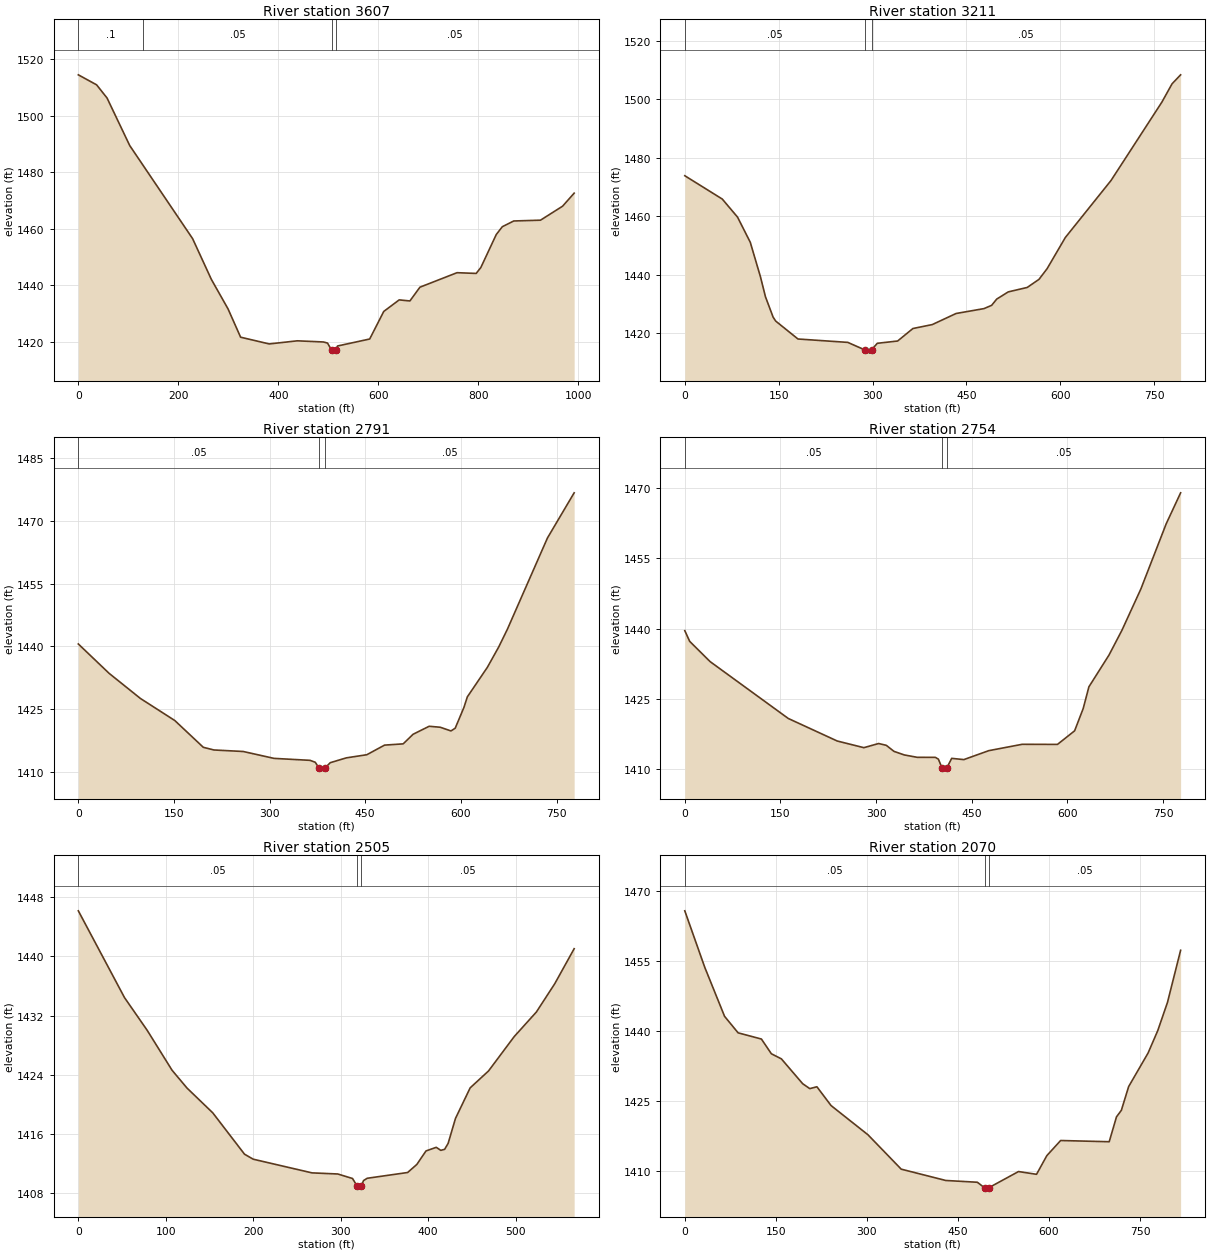
Type RM Length L Ch R = 1 ,3607    ,396.1,396.1,396.1
XS GIS Cut Line= 3
 2196707.2644638 739411.324064292196370.89163855739511.384960811
2195733.15768173739574.275679736
#Sta/Elev= 30
       0 1514.46    36.6 1510.92    57.5 1506.25   102.8 1489.46   228.6 1456.55
   266.1 1442.15   299.5 1431.71   324.6 1421.72   381.8 1419.34   438.1 1420.44
   490.4 1420.03   498.4 1419.65   506.4 1417.22   510.4 1416.09  514.66 1417.21
   518.5 1418.61   582.8 1421.08   610.9 1430.82   641.8 1434.91   663.2 1434.53
   683.3  1439.4   757.5 1444.52   795.8 1444.26   805.1 1446.35     836 1458.02
   848.1 1460.77   870.9  1462.8   924.4 1463.08   968.6 1468.02991.7675 1472.63
#Mann= 4 ,-1,0
       0      .1       0     130     .05       0   506.4    .045       0
  514.66     .05       0
Bank Sta=506.4,514.66
XS Rating Curve= 0 ,0
Exp/Cntr(USF)=0,0
Exp/Cntr=0.3,0.1

Type RM Length L Ch R = 1 ,3211    ,419.9,419.9,420.6
XS GIS Cut Line= 2
2196447.22027363739107.3366819882195666.70517846739242.190075394
#Sta/Elev= 30
       0 1473.81    59.9 1465.83    84.3 1459.65   104.6 1451.06   120.8 1439.31
   128.9 1432.41   141.1 1425.47   145.2 1424.13   180.8    1418   260.4 1416.84
  287.36 1414.29   295.4 1413.17   298.4 1414.29   307.5 1416.53     340 1417.31
   364.4 1421.58   395.4 1422.93   433.4 1426.72     478 1428.39   490.2 1429.51
   498.3 1431.64   516.7  1434.1     547 1435.62   565.8 1438.38   578.8 1442.04
   607.9 1452.69     681 1472.21   762.2 1498.99   778.4 1505.23 792.079  1508.3
#Mann= 3 ,-1,0
       0     .05       0  287.36    .045       0   298.4     .05       0
Bank Sta=287.36,298.4
XS Rating Curve= 0 ,0
Exp/Cntr(USF)=0,0
Exp/Cntr=0.3,0.1

Type RM Length L Ch R = 1 ,2791    ,37.8,37.2,36.6
XS GIS Cut Line= 6
2196347.34523982738853.5650431682196208.99889834738754.631322224
2195966.89280074738802.0873347092195908.17603953738795.652621152
2195843.02456476738711.197005711 2195670.8959771738798.869977931
#Sta/Elev= 30
       0  1440.6    48.2 1433.61    97.3 1427.62   151.4 1422.34     196 1415.97
   212.7 1415.33   258.6 1414.97   306.9 1413.33   363.4 1412.86   371.6  1412.4
   377.3 1411.07   381.3 1410.29   387.2 1411.07   395.1  1412.3   420.3 1413.45
   452.5  1414.2   480.3 1416.49   509.5 1416.79     525 1419.07   550.2 1420.98
   567.6 1420.75   584.5 1419.87   591.1 1420.52   604.8 1425.48   610.1 1427.98
   641.6 1435.05   659.5 1439.93     673 1444.13   735.8 1465.87777.6641 1476.63
#Mann= 3 ,-1,0
       0     .05       0   377.3    .045       0   387.2     .05       0
Bank Sta=377.3,387.2
XS Rating Curve= 0 ,0
Exp/Cntr(USF)=0,0
Exp/Cntr=0.3,0.1

Type RM Length L Ch R = 1 ,2754    ,250.2,249.1,246.8
XS GIS Cut Line= 6
2196356.47025815738815.5677771012196218.12391666738716.634056156
2195976.01781907738764.0900686422195917.30105786738757.655355085
2195852.14958309738673.1997396442195680.02099543738760.872711863
#Sta/Elev= 30
       0 1439.55     7.7 1437.26    39.7 1432.94   162.3 1420.79     239 1415.98
   280.9 1414.55     304 1415.44   316.1 1415.05   328.1 1413.76   344.2    1413
   364.6 1412.49     393 1412.48   397.8 1412.09  403.26 1410.26   405.2 1409.54
   409.3 1409.68   411.1 1410.26   418.6 1412.27   437.6    1412   476.7 1413.91
   529.1 1415.27   584.5 1415.25   611.4 1418.15   624.9 1422.93   633.8 1427.55
   665.3 1434.33   685.6 1439.63   715.3 1448.45     755 1462.37777.6641    1469
#Mann= 3 ,-1,0
       0     .05       0  403.26    .045       0   411.1     .05       0
Bank Sta=403.26,411.1
XS Rating Curve= 0 ,0
Exp/Cntr(USF)=0,0
Exp/Cntr=0.3,0.1

Type RM Length L Ch R = 1 ,2505    ,434.1,435.1,434
XS GIS Cut Line= 2
2196178.44370751 738452.194866152195639.03013388738626.550768737
#Sta/Elev= 30
       0 1446.18    52.8 1434.43    78.8 1429.99   107.2 1424.59   124.3 1422.18
   153.7 1418.83     190 1413.23     200 1412.55   267.2  1410.7   296.6 1410.55
   313.5 1409.94  318.74 1408.91   321.9  1408.5   323.4 1408.91   326.1 1409.66
   330.3 1409.97   376.5 1410.75     387 1411.84   397.5 1413.67   409.2 1414.16
   414.4 1413.75   418.8 1413.89   422.8 1414.69   431.2 1418.07     448 1422.21
     469  1424.5   498.4 1429.16   523.7 1432.48   544.7 1436.31566.8924 1441.05
#Mann= 3 ,-1,0
       0     .05       0  318.74    .045       0   323.4     .05       0
Bank Sta=318.74,323.4
XS Rating Curve= 0 ,0
Exp/Cntr(USF)=0,0
Exp/Cntr=0.3,0.1

Type RM Length L Ch R = 1 ,2070    ,32.9,33.2,34.6
XS GIS Cut Line= 6
2196076.20581255737868.3438785482195772.34433901738153.338136413
2195721.15127282738175.505236984 2195651.6563664738200.118016341
2195605.51843196738211.9258061492195382.52369952738209.883841644
#Sta/Elev= 30
       0  1465.7    32.9 1453.61    65.5 1443.13    87.8  1439.6   126.2 1438.27
   142.6 1435.12   159.1 1434.03   194.2 1428.71   205.9 1427.66   217.6 1428.06
     241 1424.03   301.7 1417.79   356.5 1410.43   429.9 1408.01   481.9 1407.63
  493.91 1406.43   496.4 1406.16  500.32 1406.43   549.7 1409.92   579.4 1409.33
   596.4 1413.33   619.1 1416.56   699.1  1416.3   711.1 1421.62   719.1 1423.02
   731.1 1428.09   763.1 1435.27   779.1 1440.08   795.1 1446.12816.7375 1457.26
#Mann= 3 ,-1,0
       0     .05       0  493.91    .045       0  500.32     .05       0
Bank Sta=493.91,500.32
XS Rating Curve= 0 ,0
Exp/Cntr(USF)=0,0
Exp/Cntr=0.3,0.1

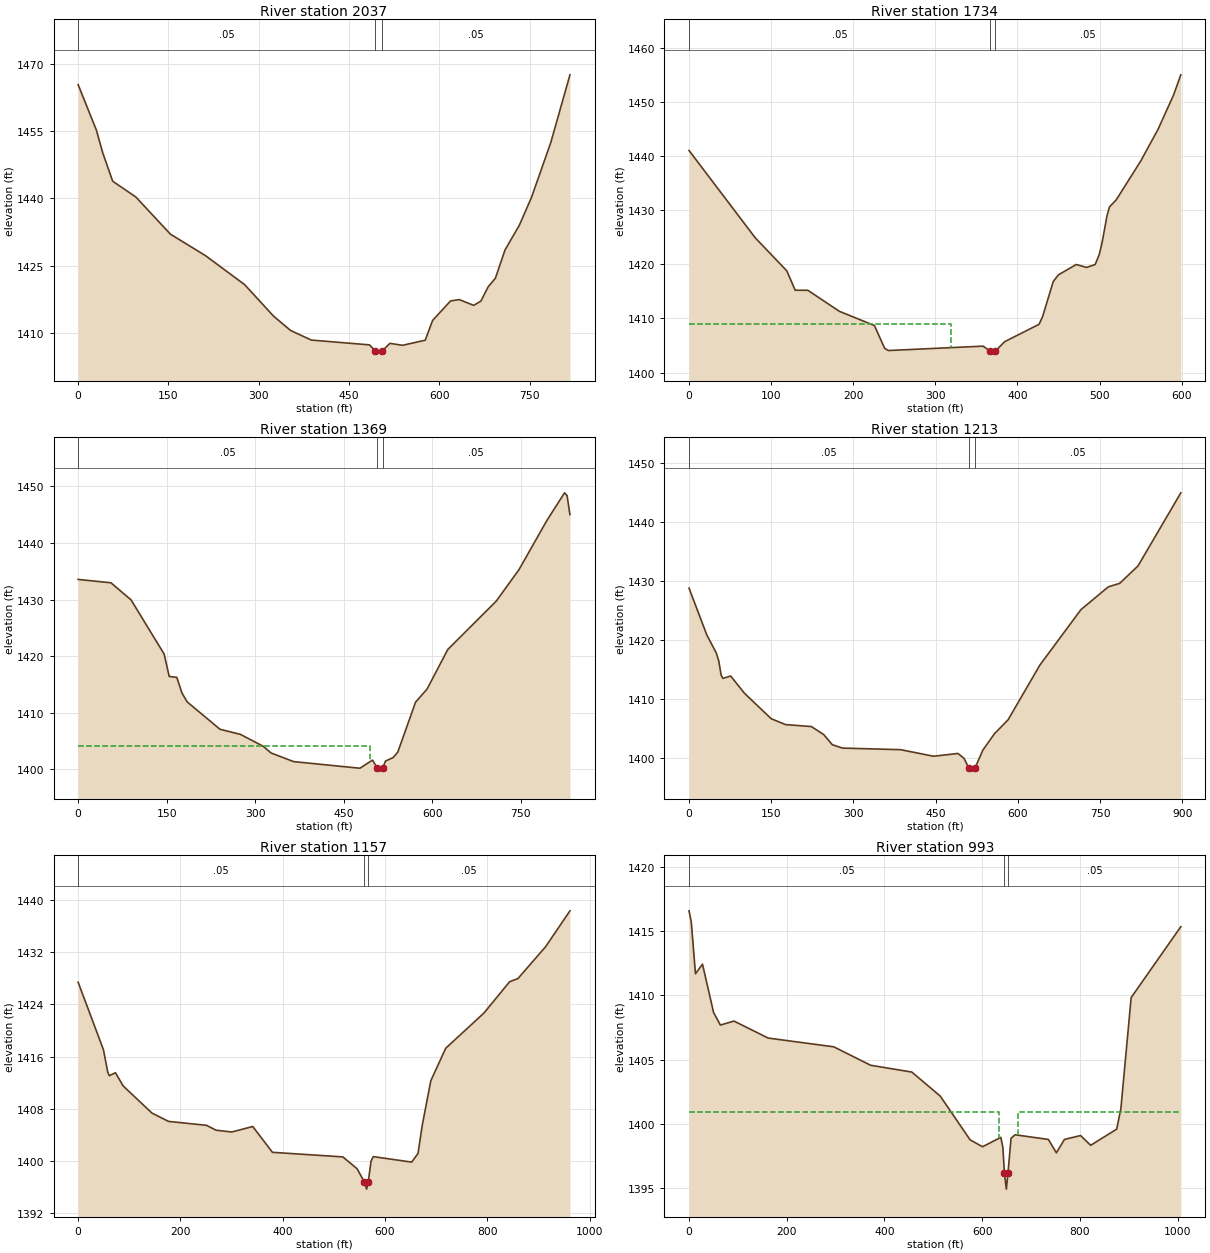
Type RM Length L Ch R = 1 ,2037    ,302.7,302.7,301.6
XS GIS Cut Line= 6
2196054.02933928737844.2724843662195750.16786573738129.266742231
2195698.97479955738151.4338428022195629.47989313738176.046622159
2195583.34195869738187.8544119672195360.34722625738185.812447462
#Sta/Elev= 30
       0  1465.3    30.3 1455.16    40.9 1450.09    57.4 1443.78    95.8 1440.27
   153.3 1431.98   211.8 1427.17   276.5 1420.74   324.6 1413.71   352.9 1410.52
   387.2 1408.39   483.8 1407.32   493.8 1405.93   496.6 1405.48  504.61 1405.93
   517.8 1407.66   538.6 1407.22   576.4 1408.36   588.7 1412.77   618.5 1417.11
   632.9 1417.41   656.9 1416.12   668.9 1417.08   680.9 1420.25   692.9 1422.16
   708.9 1428.46   732.9 1434.03   752.9 1440.18   784.9 1452.39816.7375 1467.48
#Mann= 3 ,-1,0
       0     .05       0   493.8    .045       0  504.61     .05       0
Bank Sta=493.8,504.61
XS Rating Curve= 0 ,0
Exp/Cntr(USF)=0,0
Exp/Cntr=0.3,0.1

Type RM Length L Ch R = 1 ,1734    ,365.2,365.6,365.2
XS GIS Cut Line= 2
 2195871.8482926737770.5829100752195310.36780006737978.992699886
#Sta/Elev= 30
       0 1441.01    80.7 1424.88   119.1 1418.79   129.3 1415.21   144.7  1415.2
   183.1 1411.32   225.8 1408.69   238.3 1404.48   242.9 1404.08   358.1 1404.89
   366.6 1403.99   370.9  1403.6  373.05 1403.99   384.5 1405.72   426.3 1408.92
   430.6 1410.35   443.6 1416.83   449.8 1418.04   471.6 1419.96   484.1 1419.42
   494.6 1419.95   499.6  1421.8   503.1 1424.06     509 1428.94   512.1  1430.6
   520.2 1431.88   550.1 1439.06   571.2 1444.92   589.9 1451.18598.9115 1454.97
#Mann= 3 ,-1,0
       0     .05       0   366.6    .045       0  373.05     .05       0
#XS Ineff= 2 , 0
          319.16 1409.04
Permanent Ineff=
       F       F
Bank Sta=366.6,373.05
XS Rating Curve= 0 ,0
Exp/Cntr(USF)=0,0
Exp/Cntr=0.3,0.1

Type RM Length L Ch R = 1 ,1369    ,155.1,155.8,155.3
XS GIS Cut Line= 6
2195827.58693017 737392.296930092195559.11404192737499.445337832
2195408.16486876737559.6194300952195315.16702326737596.381823748
2195245.51263501737624.1885266752195171.91850485 737817.78370247
#Sta/Elev= 30
       0 1433.55    55.6 1432.96    89.8 1429.93   145.8 1420.36   154.4 1416.41
   167.3 1416.24   175.9  1413.5   184.9  1411.9   240.5 1407.07     275 1406.17
   313.8 1404.06     327 1402.88   365.4 1401.35   477.6 1400.18     499 1401.62
  507.25 1400.19   511.8 1399.67   516.1 1400.19   521.1 1401.46   534.1 1402.07
   541.9 1403.04     572 1411.87   591.4 1414.16   626.6 1421.17   708.9 1429.74
   747.4  1435.3   794.5 1443.96   824.5 1448.86   828.8 1448.38833.6774 1445.01
#Mann= 3 ,-1,0
       0     .05       0  507.25    .045       0   516.1     .05       0
#XS Ineff= 2 , 0
          494.49 1404.12
Permanent Ineff=
       F       F
Bank Sta=507.25,516.1
XS Rating Curve= 0 ,0
Exp/Cntr(USF)=0,0
Exp/Cntr=0.3,0.1

Type RM Length L Ch R = 1 ,1213    ,56.8,56.2,56
XS GIS Cut Line= 4
2195770.06937243737396.4478393822195598.43778082737322.891442979
 2195242.9151982737459.1069918742195153.01293593737776.489220801
#Sta/Elev= 30
       0 1428.81    32.5 1420.87    49.9  1417.8    54.3 1416.47    58.6 1414.08
    61.8 1413.52      76 1413.92   101.4 1410.98     150 1406.69   176.1  1405.7
   223.4 1405.36     246 1403.99   261.5 1402.29   280.1 1401.72   386.2 1401.45
   446.2 1400.34   490.7 1400.81   501.9 1399.97   510.4 1398.36   517.3 1397.82
  521.91 1398.36   536.1 1401.37   557.5 1404.17   582.1  1406.5   640.3 1415.79
   715.1 1425.16     765 1429.01   785.8 1429.61   819.1 1432.54897.3234 1444.93
#Mann= 3 ,-1,0
       0     .05       0   510.4    .045       0  521.91     .05       0
Bank Sta=510.4,521.91
XS Rating Curve= 0 ,0
Exp/Cntr(USF)=0,0
Exp/Cntr=0.3,0.1

Type RM Length L Ch R = 1 ,1157    ,162.4,163.1,163.7
XS GIS Cut Line= 4
2195781.29872347737384.6104357522195552.55904904737281.293489145
2195197.03646642737417.5090380412195107.13420415737734.891266968
#Sta/Elev= 30
       0 1427.37    49.5 1417.04    57.9 1413.64    60.9 1413.07      73 1413.52
    88.1  1411.5   144.4 1407.35   176.8 1406.08     251 1405.48   269.8 1404.73
   300.5 1404.46   341.4  1405.3   379.9 1401.35   517.5 1400.65   545.4 1398.84
   559.8 1396.79     564 1395.72  567.17 1396.79   572.7 1400.01     577 1400.69
   652.2 1399.85   664.5 1401.18   672.9 1405.53   689.6 1412.31   718.7 1417.27
   793.5 1422.66   843.4 1427.43     860 1427.94   914.1 1432.81961.5843 1438.29
#Mann= 3 ,-1,0
       0     .05       0   559.8    .045       0  567.17     .05       0
Bank Sta=559.8,567.17
XS Rating Curve= 0 ,0
Exp/Cntr(USF)=0,0
Exp/Cntr=0.3,0.1

Type RM Length L Ch R = 1 ,993     ,840.6,840.6,840.6
XS GIS Cut Line= 4
2195767.53932534737339.5665726022195475.15264963737167.444605018
2195104.42841176737275.5725077312195035.74634583737548.155460635
#Sta/Elev= 30
       0 1416.56     4.7 1415.69    13.2 1411.67    27.6 1412.42    50.3 1408.67
    64.2 1407.69    92.1    1408     162 1406.68   296.3    1406   371.6 1404.57
     456 1404.04   514.1 1402.18   575.3 1398.78   600.7 1398.24   638.2 1398.97
   642.4 1398.19   645.5  1396.2   649.5 1394.95   652.8  1396.2   659.1  1398.9
   667.4 1399.17   735.4 1398.81   751.9 1397.77   768.4 1398.81   801.4 1399.11
     822 1398.35   875.3 1399.61   883.9 1401.21   904.9 1409.821006.561 1415.33
#Mann= 3 ,-1,0
       0     .05       0   645.5    .045       0   652.8     .05       0
#XS Ineff= 2 , 0
          634.36 1400.92  672.69         1400.92
Permanent Ineff=
       F       F
Bank Sta=645.5,652.8
XS Rating Curve= 0 ,0
Exp/Cntr(USF)=0,0
Exp/Cntr=0.3,0.1

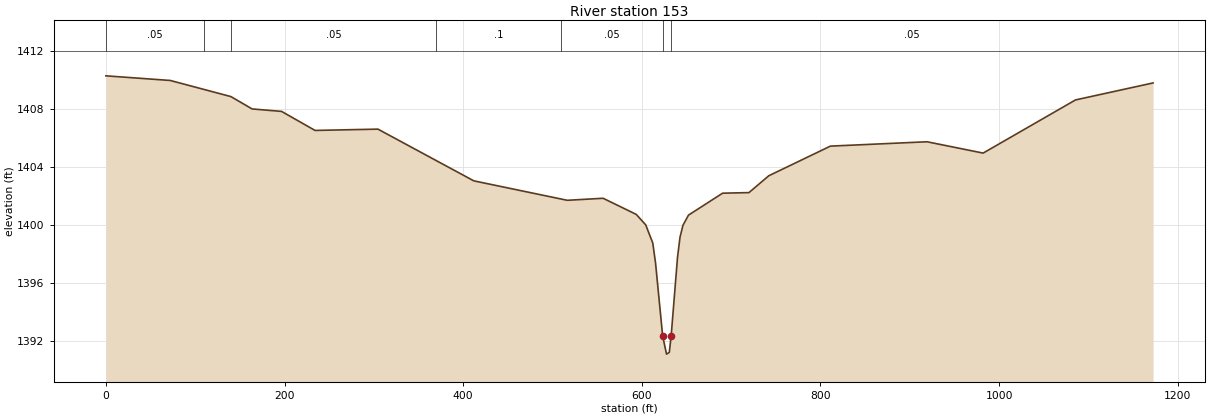
Type RM Length L Ch R = 1 ,153     ,,,
XS GIS Cut Line= 4
2195485.10965456 737062.090191852195079.82635476736692.122034355
2194760.30840056736564.3148526752194597.18607657736791.340767501
#Sta/Elev= 30
       0 1410.28    72.1 1409.96     140 1408.85   163.7    1408   196.7 1407.83
   234.2 1406.52   304.6 1406.61   411.9 1403.05   516.6 1401.71   556.7 1401.85
   593.8 1400.74   604.4 1400.02   612.3 1398.77   615.4  1397.4  623.37 1392.37
   627.7 1391.12   630.8 1391.24  632.89 1392.37     640 1397.78   642.8 1399.17
   646.1 1399.99   652.3 1400.69   690.5  1402.2     720 1402.24   742.2  1403.4
   811.2 1405.44   919.4 1405.74   982.2 1404.96  1085.6 1408.621172.438 1409.79
#Mann= 7 ,-1,0
       0     .05       0     110      .1       0     140     .05       0
     370      .1       0     510     .05       0  623.37    .045       0
  632.89     .05       0
Bank Sta=623.37,632.89
XS Rating Curve= 0 ,0
Exp/Cntr(USF)=0,0
Exp/Cntr=0.3,0.1
LCMann Table=0

Chan Stop Cuts=-1
Use User Specified Reach Order=0
Composite Channel Slope=5